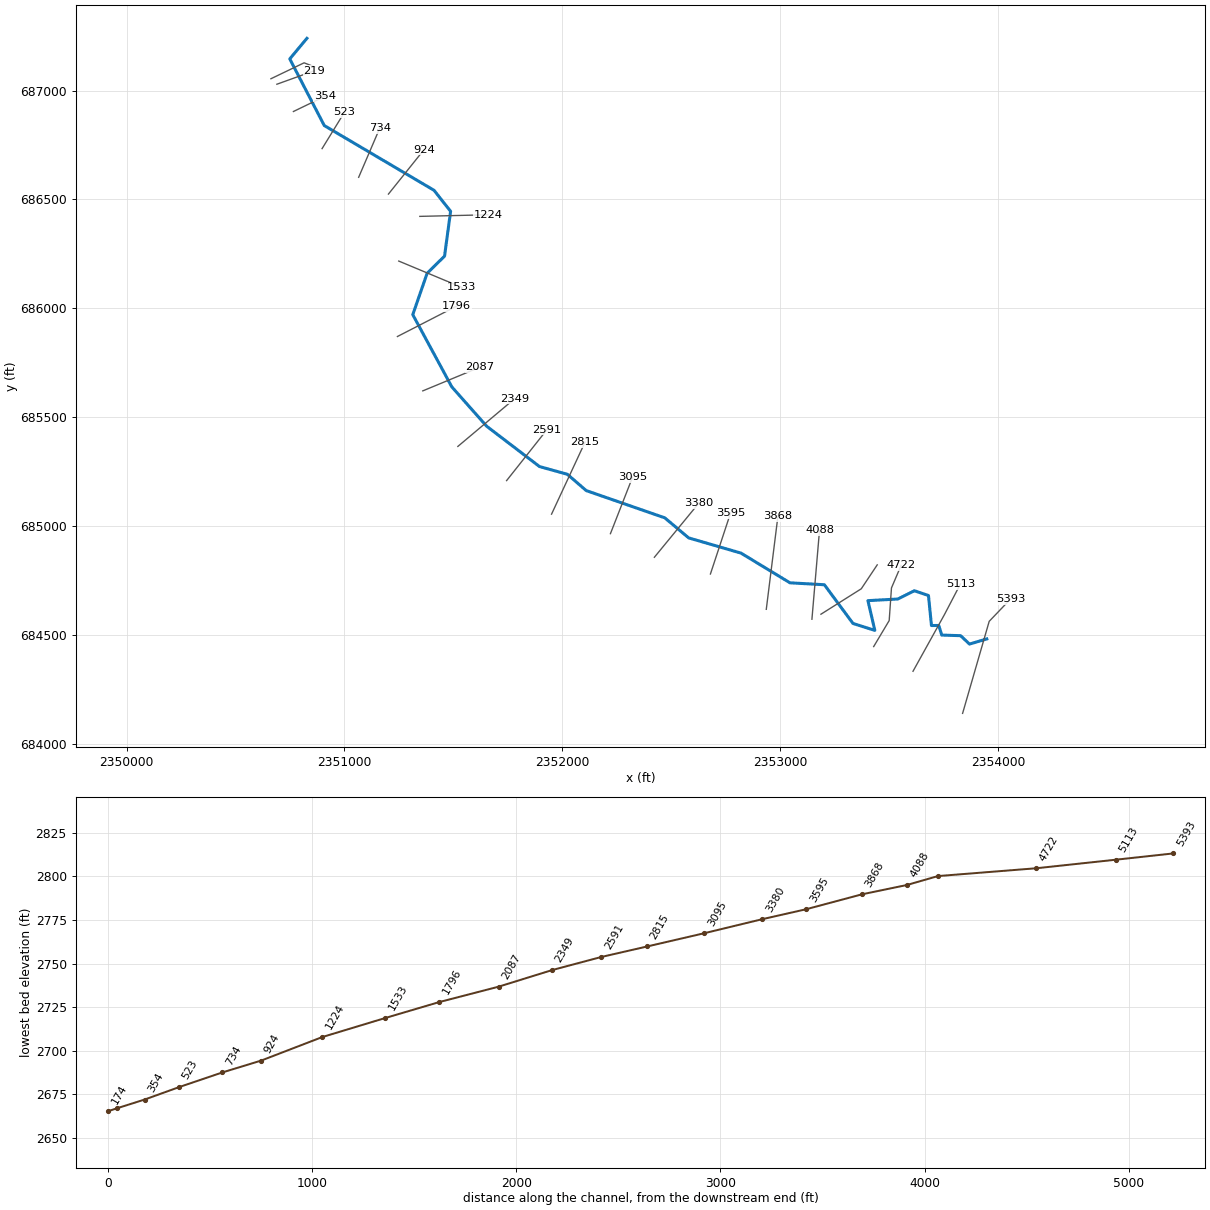
--- LAURLLCKRN.prj (project) ---

Proj Title=LAURLLCKRN
Current Plan=p01
Default Exp/Contr=0,0
English Units
Geom File=g01
Flow File=f01
Plan File=p01
BEGIN DESCRIPTION:
----------MODEL BY WOOD PLC 2022----------
AFH study
Randolph County, WV
HEC-RAS Version: RAS 6.2
Vertical Datum: NAVD88
Projection: NAD 1983 StatePlane West Virginia S FIPS 4702 (US Feet)
Terrain: 1-meter LIDAR (FEMA Region III 3DEP collected 2016-2018)
Land Use: 2019 NLCD
Hydrologic Method:
WV SIR2010-5033 regression equations
Additional Model Notes:
None
END DESCRIPTION:
DSS File=dss
DSS Export Rating Curves= 0
DSS Export Rating Curve Sorted= 0
DSS Export Volume Flow Curves= 0
DXF OffsetX= 0
DXF OffsetY= 0
DXF ScaleX= 0
DXF ScaleY= 0

--- LAURLLCKRN.p01 (plan) ---

Plan Title=Floodplain
Program Version=6.20
Short Identifier=Floodplain
Geom File=g01
Flow File=f01
Subcritical Flow
K Sum by GR= 0
Std Step Tol= 0.01
Critical Tol= 0.01
Num of Std Step Trials= 20
Max Error Tol= 0.3
Flow Tol Ratio= 0.001
Split Flow NTrial= 30
Split Flow Tol= 0.02
Split Flow Ratio= 0.02
Log Output Level= 0
Friction Slope Method= 1
Unsteady Friction Slope Method= 2
Unsteady Bridges Friction Slope Method= 1
Parabolic Critical Depth
Global Vel Dist= 0 , 0 , 0
Global Log Level= 0
CheckData=True
Encroach Param=-1 ,0,0, 0
Computation Interval=0.1SEC
Output Interval=1SEC
Instantaneous Interval=Max Profile
Mapping Interval=1HOUR
Computation Time Step Use Courant=        0
Computation Time Step Use Time Series=    0
Computation Time Step Count To Double=0
Computation Time Step Max Doubling=0
Computation Time Step Max Halving=0
Computation Time Step Residence Courant=0
Run HTab= 0
Run UNet= 0
Run Sediment= 0
Run PostProcess= 0
Run WQNet= 0
Run RASMapper=-1
UNET Theta= 0
UNET Theta Warmup= 0
UNET ZTol= 0
UNET ZSATol= 0
UNET MxIter= 0
UNET Max Iter WO Improvement= 0
UNET MaxInSteps= 0
UNET DtIC= 0
UNET DtMin= 0
UNET MaxCRTS= 0
UNET WFStab= 0
UNET SFStab= 0
UNET WFX= 1
UNET SFX= 1
UNET Gravity=32.174
UNET 1D Methodology=Finite Difference
UNET DSS MLevel= 1
UNET Pardiso=0
UNET DZMax Abort= 0
UNET Use Existing IB Tables= 0
UNET Froude Reduction=False
UNET Froude Limit= 0
UNET Froude Power= 0
UNET D1 Cores= 0
UNET WindReference=Eulerian
UNET WindDragFormulation=Hsu (1988)
UNET D2 Coriolis=0
UNET D2 Cores= 0
UNET D2 Theta= 1
UNET D2 Theta Warmup= 1
UNET D2 Z Tol= 0.01
UNET D2 Volume Tol= 0.01
UNET D2 Max Iterations= 20
UNET D2 Equation= 0
UNET D2 RampUpFraction=0.1
UNET D2 TimeSlices= 1
UNET D2 Turbulence Formulation=Non-Conservative (original)
UNET D2 Eddy Viscosity=0.3
UNET D2 Transverse Eddy Viscosity=0.1
UNET D2 Smagorinsky Mixing=0
UNET D2 BCVolumeCheck=0
UNET D2 Cores=0
UNET D2 SolverType=PARDISO (Direct)
UNET D2 Minimum Iterations= 2147483647
UNET D2 Maximum Iterations= 2147483647
UNET D2 Restart Number= 10
UNET D2 Relaxation Coeff=1.3
UNET D2 SOR Precondition Iterations= 10
UNET D2 ILUT Maximum Fill= 8
UNET D2 ILUT Tolerance=1E-08
UNET D1D2 MaxIter= 0
UNET D1D2 ZTol=0.01
UNET D1D2 QTol=0.1
UNET D1D2 MinQTol=1
DSS File=dss
Write IC File= 0
Write IC File at Fixed DateTime=0
Write IC File at Sim End=0
Echo Input=False
Echo Parameters=False
Echo Output=False
Write Detailed= 0
HDF Write Warmup=0
HDF Write Time Slices=0
HDF Flush=0
HDF Compression= 1
HDF Chunk Size= 1
HDF Spatial Parts= 1
HDF Use Max Rows=0
HDF Fixed Rows= 1
Calibration Method= 0
Calibration Iterations= 20
Calibration Max Change=0.05
Calibration Tolerance=0.2
Calibration Maximum=1.5
Calibration Minimum=0.5
Calibration Optimization Method= 1
WQ AD Non Conservative
WQ ULTIMATE=-1
WQ Max Comp Step=1HOUR
WQ Output Interval=15MIN
WQ Output Selected Increments= 0
WQ Output face flow=0
WQ Output face velocity=0
WQ Output face area=0
WQ Output face dispersion=0
WQ Output cell volume=0
WQ Output cell surface area=0
WQ Output cell continuity=0
WQ Output cumulative cell continuity=0
WQ Output face conc=0
WQ Output face dconc_dx=0
WQ Output face courant=0
WQ Output face peclet=0
WQ Output face adv mass=0
WQ Output face disp mass=0
WQ Output cell mass=0
WQ Output cell source sink temp=0
WQ Output nsm pathways=0
WQ Output nsm derived pathways=0
WQ Create Restart=0
WQ Fixed Restart=0
WQ System Summary=0
WQ Write To DSS=0
Sorting and Armoring Iterations= 10
XS Update Threshold= 0.02
Bed Roughness Predictor= 0
Hydraulics Update Threshold= 0.02
Energy Slope Method= 1
Volume Change Method= 1
Sediment Retention Method= 0
Sediment TS Multiplier= 1
Warm Up Method= 0
XS Weighting Method= 0
Number of US Weighted Cross Sections= 1
Number of DS Weighted Cross Sections= 1
Upstream XS Weight=0
Main XS Weight=1
Downstream XS Weight=0
Number of DS XS's Weighted with US Boundary= 1
Upstream Boundary Weight= 1
Weight of XSs Associated with US Boundary= 0
Number of US XS's Weighted with DS Boundary= 1
Downstream Boundary Weight= 0.5
Weight of XSs Associated with DS Boundary= 0.5
Percentile Method= 0
Sediment Output Level= 3
Mass or Volume Output= 0
Output Increment Type= 1
Profile and TS Output Increment= 1
Transport Output Increment 1
XS Output Flag= 0
XS Output Increment= 10
Read HDF5 Sediment Hotstart= 0
Sediment Hotstart Type= 0
Write Gradation File= 0
Read Gradation Hotstart= 0
Write HDF5 File= 1
Write Binary Output= 1
Write DSS Sediment File= 0
DSS Sediment Output Type= 1
SV Curve= 0
Specific Gage Flag= 0
Subcell Erosion Methods= 0
Subcell Deposition Methods= 0
Advection Scheme= 1
Matrix Solver= 0
Implicit Weighting Factor= 1
Maximum Outer Loop Convergence Iterations= 5
Convergence Maximum Absolute= 0.001
Convergence RMSE= 0.0001
Grain Fractions Max Abs Error= 0.001
Max Subgrid Regions= 1
Max Subgrid Length Scale= 3.402823E+38
Initial Layer Thickness= 3.402823E+38
Min Layer Thickness= 3.402823E+38
Max Layer Thickness= 3.402823E+38
Number of Layers= 5

--- LAURLLCKRN.f01 (steady flow) ---

Flow Title=Flow
Program Version=6.20
Number of Profiles= 1
Profile Names=P100yr
River Rch & RM=LAURLLCKRN,Main,5393
     350
Boundary for River Rch & Prof#=LAURLLCKRN,Main            , 1
Up Type= 0
Dn Type= 3
Dn Slope=0.03862
DSS Import GetInterval= 0
DSS Import GetPeak= 0
DSS Import FillOption= 0

--- LAURLLCKRN.g01 (geometry) ---

Geom Title=Geometry
Program Version=6.20

River Reach=LAURLLCKRN      ,Main
Reach XY= 30
2353948.24700001684482.8770000042353869.08100002684459.266000003
2353828.10900003684497.8080000132353741.64999999 684500.58600001
2353727.89886296684544.648867654     2353694.428684544.335999995
2353680.68200001684682.1009999962353616.03123061 684704.04507516
2353540.09423335684666.1251378532353402.81900005684658.543000013
2353434.50300001684522.0409999942353334.15600002684553.899000019
2353202.77405065684731.6873734952353045.09300001684740.356999993
2352820.09300002      684876.8162352579.98900001684946.606999993
2352470.09400001685038.7950000172352109.67700003685163.795000002
2352023.03149555 685238.583159232351895.09300002685274.212000012
2351652.90600005 685458.98008945      2351492.75685639.750000015
2351313.49600002685971.3470000182351379.46800001686161.451000005
2351459.32900004686240.0100000052351487.10700002686445.738999993
2351411.15200002686542.0929999952350907.24599999686839.401999995
2350748.82600003 687145.39200002     2350827.576      687239.783

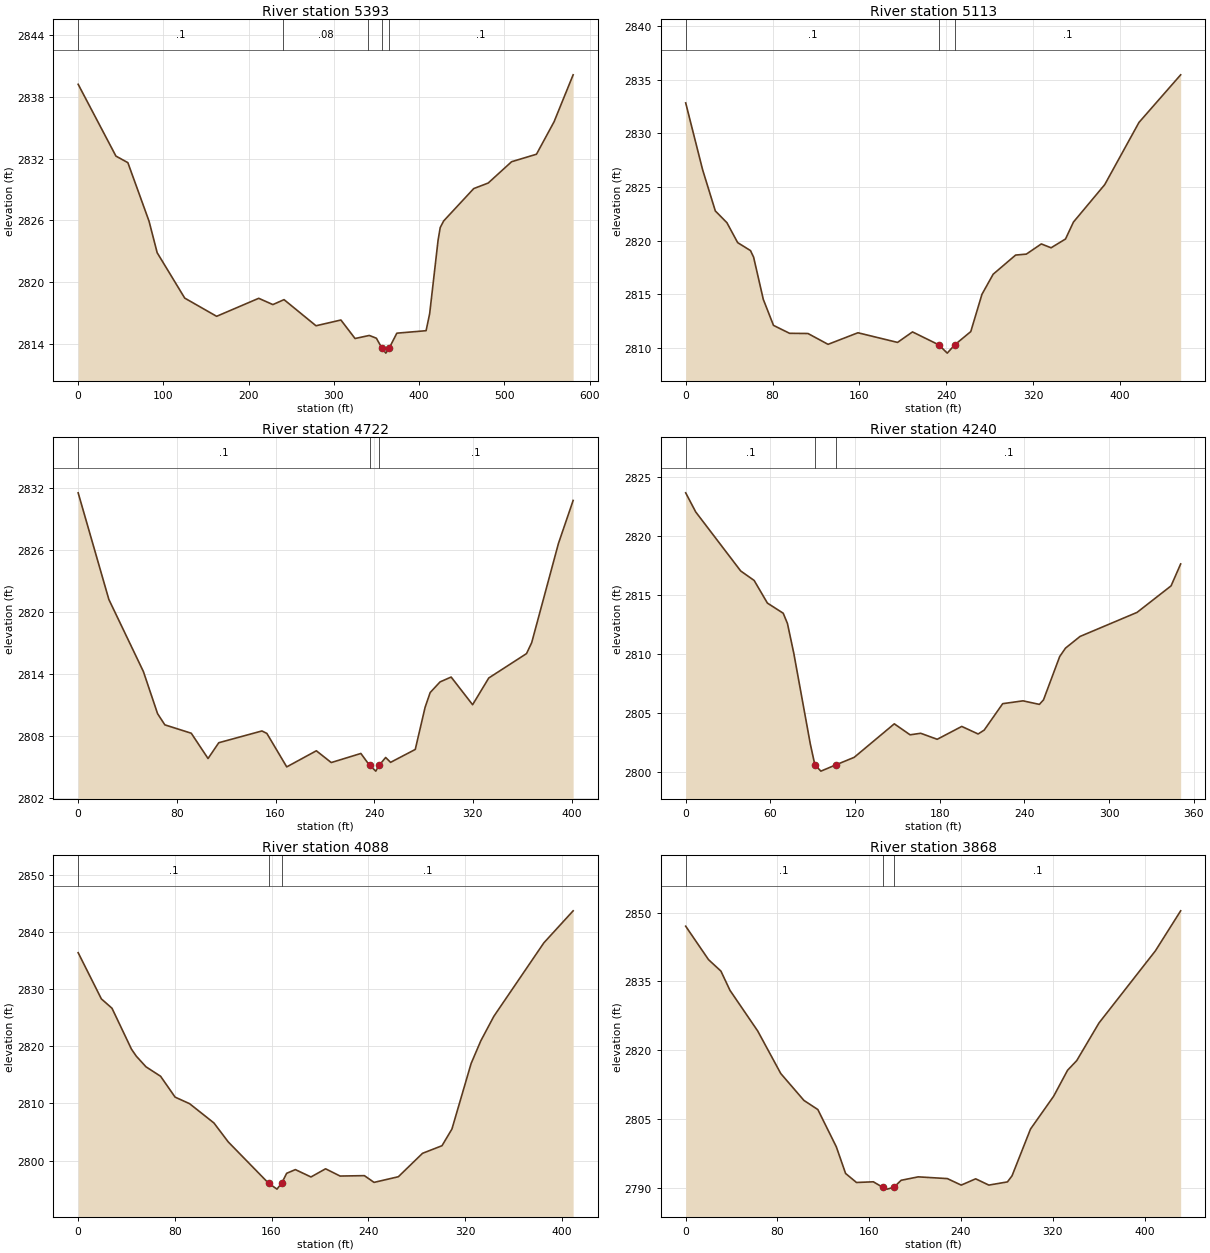
Type RM Length L Ch R = 1 ,5393    ,278.2,280.4,275.2
XS GIS Cut Line= 3
2353837.37353641684141.1329413362353959.46788419684563.640280254
 2354056.8060517684665.373942965
#Sta/Elev= 30
       0 2839.23    44.3 2832.25    58.3 2831.61    83.1 2825.93    92.7 2822.85
     125 2818.44   162.4 2816.67   211.8 2818.42   228.4 2817.81   241.5 2818.29
     279 2815.75   308.2 2816.31   324.8 2814.51   341.5 2814.81   349.8 2814.54
   356.52813.545   360.9 2813.09  364.69 2813.55   373.8 2815.03   408.1 2815.27
   412.3 2816.92   422.2 2824.08   424.7  2825.3   428.7 2825.94     464 2829.09
     481 2829.63   508.4  2831.7   537.6 2832.43   558.2 2835.58   580.6 2840.15
#Mann= 5, -1 ,  0
       0     0.1       0     240    0.08       0     340     0.1       0
   356.5   0.045       0  364.69     0.1       0
Bank Sta=356.5,364.69
XS Rating Curve= 0 ,0
Exp/Cntr(USF)=0,0
Exp/Cntr=0.3,0.1

Type RM Length L Ch R = 1 ,5113    ,381.8,390.8,385.7
XS GIS Cut Line= 3
2353609.75076858684334.4434468282353753.36522605684593.336116464
2353827.41896724684735.220220744
#Sta/Elev= 30
       0 2832.85    15.6 2826.61    27.3 2822.77      38 2821.67    47.9 2819.81
    59.7 2819.07    62.6 2818.45    71.5 2814.52    80.9 2812.09    95.7 2811.35
   112.7 2811.33   131.2 2810.32   158.7  2811.4   195.2  2810.5     209 2811.48
   233.3 2810.27     241  2809.5     248 2810.28   262.7 2811.51     273 2814.99
   283.3 2816.86     304 2818.65   313.9 2818.74   327.7 2819.69   336.7 2819.33
     350 2820.15   357.3 2821.73   386.1 2825.22   417.7 2831.03   456.1 2835.47
#Mann= 3, -1 ,  0
       0     0.1       0   233.3   0.045       0     248     0.1       0
Bank Sta=233.3,248
XS Rating Curve= 0 ,0
Exp/Cntr=0.3,0.1

Type RM Length L Ch R = 1 ,4722    ,483.5,482.2,462.6
XS GIS Cut Line= 4
2353429.21303836684447.7913610722353500.38572084 684567.09871814
2353510.82029211684716.7711019442353554.83700771684820.083947522
#Sta/Elev= 30
       0 2831.54    24.9 2821.21    52.9 2814.23    64.4 2810.15    70.3 2809.07
    91.7 2808.26   105.3 2805.81     114 2807.34     149 2808.48     153 2808.24
   169.1    2805   193.1 2806.56   205.2 2805.42   229.2  2806.3   236.2 2805.16
   241.3 2804.59  243.93 2805.14   249.3 2805.91   253.3 2805.44   273.3 2806.69
   281.3 2810.78   285.4  2812.2   293.4 2813.23   302.4  2813.7   319.8 2811.02
   332.9 2813.61   363.5 2815.97   367.7 2817.03   389.4 2826.64   401.3  2830.8
#Mann= 3, -1 ,  0
       0     0.1       0   236.2   0.045       0  243.93     0.1       0
Bank Sta=236.2,243.93
XS Rating Curve= 0 ,0
Exp/Cntr(USF)=0,0
Exp/Cntr=0.3,0.1

Type RM Length L Ch R = 1 ,4240    ,146.4,152,157.6
XS GIS Cut Line= 3
2353187.17568502 684596.343619292353372.24110202 684713.04531882
 2353445.4386177684822.841592342
#Sta/Elev= 30
       0  2823.7     7.1 2822.08      39 2817.07    48.5 2816.27    57.9 2814.35
    69.1 2813.49    72.1 2812.62    76.6 2810.09    88.3  2802.4   91.55 2800.62
    95.8  2800.1   106.6 2800.64   119.4 2801.27   147.8 2804.11     159 2803.18
   166.5 2803.31   178.2  2802.8   195.6 2803.89   207.2 2803.25   211.5 2803.58
   224.6 2805.82     239 2806.06   250.6 2805.76   253.5 2806.14     265 2809.82
   269.1 2810.53   279.4 2811.52   319.8 2813.56   343.9 2815.81   350.7 2817.67
#Mann= 3, -1 ,  0
       0     0.1       0   91.55   0.045       0   106.6     0.1       0
Bank Sta=91.55,106.6
XS Rating Curve= 0 ,0
Exp/Cntr(USF)=0,0
Exp/Cntr=0.3,0.1

Type RM Length L Ch R = 1 ,4088    ,220.1,220,219.6
XS GIS Cut Line= 2
2353145.75294826684573.2657979942353180.51635026684981.260922054
#Sta/Elev= 30
       0 2836.39    19.2  2828.3      28 2826.66    44.1  2819.5    48.1 2818.27
    56.1 2816.41    68.2 2814.75    80.2  2811.1    92.2 2809.95   112.3 2806.58
   124.2 2803.25   157.5 2796.03   164.5 2794.99   168.5 2796.08   172.5 2797.76
   179.7 2798.41   192.6 2797.12   204.7 2798.55   216.7 2797.28   236.8 2797.35
   244.8 2796.17   264.9 2797.16   284.9 2801.26     301 2802.59   309.2  2805.5
   325.1 2816.99   333.1 2820.95   343.9 2825.25   385.3 2838.12   409.5 2843.72
#Mann= 3, -1 ,  0
       0     0.1       0   157.5   0.045       0   168.5     0.1       0
Bank Sta=157.5,168.5
XS Rating Curve= 0 ,0
Exp/Cntr=0.3,0.1

Type RM Length L Ch R = 1 ,3868    ,272.9,273.1,272.8
XS GIS Cut Line= 2
2352936.22529431684618.8711584232352989.75163753 685047.08190418
#Sta/Elev= 30
       0 2847.07    19.9 2839.77    30.7 2837.27    38.6 2833.07    62.8 2824.18
    82.9 2814.89   103.1 2809.02   115.2 2807.03   131.3  2798.9   139.4 2793.07
   148.9  2791.1   163.6 2791.25   171.6 2790.07   175.7 2789.65   181.62790.077
   187.8 2791.58   202.7 2792.33   228.1 2791.95   240.2 2790.53   252.8  2791.9
   264.3 2790.53   280.5 2791.23   284.5 2792.56   300.6 2802.77   320.8 2809.95
   332.9 2815.61   340.9 2817.72   360.3 2825.94   409.5  2841.7   431.5 2850.43
#Mann= 3, -1 ,  0
       0     0.1       0   171.6   0.045       0   181.6     0.1       0
Bank Sta=171.6,181.6
XS Rating Curve= 0 ,0
Exp/Cntr(USF)=0,0
Exp/Cntr=0.3,0.1

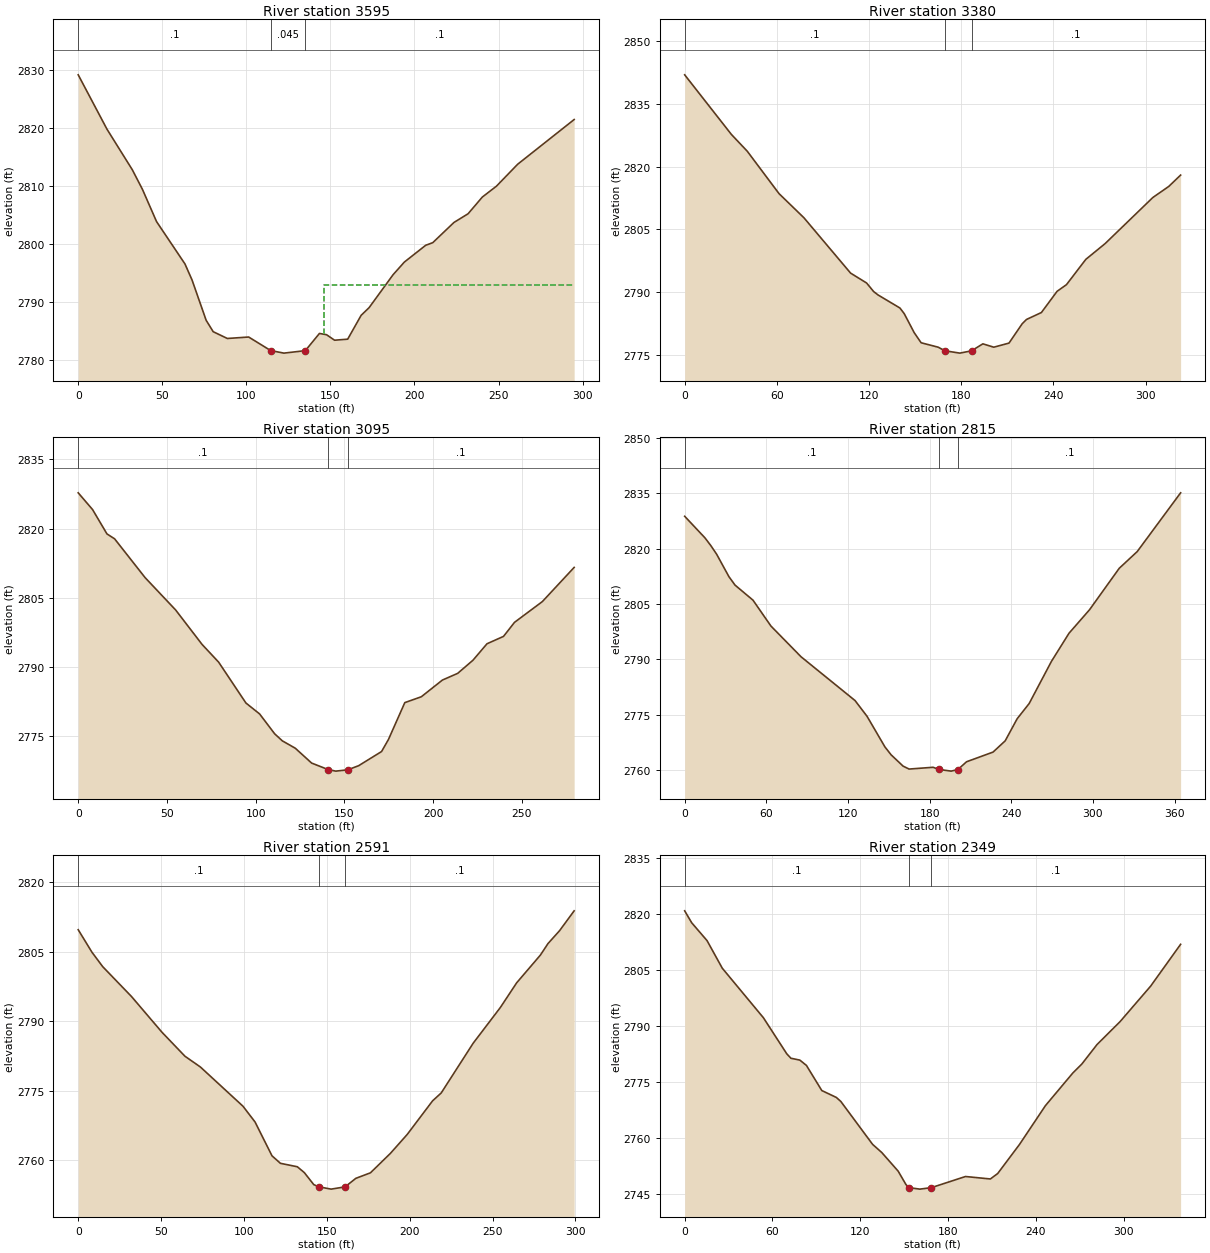
Type RM Length L Ch R = 1 ,3595    ,216.8,214.5,210.3
XS GIS Cut Line= 2
2352679.81422096 684780.927681422352772.29662903685061.035794338
#Sta/Elev= 30
       0 2829.16    17.1 2819.78    32.2 2812.76    38.2 2809.39    46.6 2803.82
    63.5 2796.51    67.7 2793.75    76.1 2786.78    80.3 2784.81    88.7 2783.64
   101.4 2783.89   114.5 2781.55   122.4 2781.11   135.1 2781.54   143.5 2784.51
   147.7 2784.29   152.5 2783.34   160.3 2783.52   168.3 2787.64     173 2788.95
   187.3 2794.65     194 2796.83   206.7 2799.73   210.9 2800.18   223.5 2803.67
   231.9 2805.17   240.4 2808.06   248.8 2809.94   261.4 2813.72     295 2821.44
#Mann= 3, -1 ,  0
       0     0.1       0   114.5   0.045       0   135.1     0.1       0
#XS Ineff= 2 , 0
                          145.99         2792.94
Permanent Ineff=
       F       F
Bank Sta=114.5,135.1
XS Rating Curve= 0 ,0
Exp/Cntr=0.3,0.1

Type RM Length L Ch R = 1 ,3380    ,282.7,285.1,288.2
XS GIS Cut Line= 2
 2352422.4934979684857.6951923722352627.34740405685107.154384537
#Sta/Elev= 30
       0 2841.96    30.4 2827.71    40.7 2823.71    61.4 2813.56    77.6 2807.79
     108 2794.55   118.4 2792.19     123 2790.14   125.9 2789.32   140.1 2786.21
   142.9 2784.86   149.4 2780.31   153.9  2777.9     165 2776.84   169.42775.984
   179.1 2775.42   186.7 2775.97   194.1 2777.64   201.2 2776.84   211.1 2777.82
   219.7 2782.45   222.5 2783.47   232.2 2785.13   242.4  2790.2   248.5 2791.79
   261.1 2797.84   273.7 2801.62   304.7 2812.62   315.1 2815.28   322.8 2817.99
#Mann= 3, -1 ,  0
       0     0.1       0   169.4   0.045       0   186.7     0.1       0
Bank Sta=169.4,186.7
XS Rating Curve= 0 ,0
Exp/Cntr(USF)=0,0
Exp/Cntr=0.3,0.1

Type RM Length L Ch R = 1 ,3095    ,279.5,279.6,279
XS GIS Cut Line= 2
2352220.84161539684966.0584631972352322.71884943685226.266081842
#Sta/Elev= 30
       0 2827.75     8.1 2824.11    16.2 2818.83    20.5 2817.77    37.7 2809.34
    54.9 2802.32    69.8 2794.84    79.1 2791.01    94.5 2782.13   102.2 2779.76
   110.7 2775.44     115 2773.92   122.3 2772.32   131.5  2769.1   140.8 2767.69
   145.1 2767.35   151.8 2767.63     158 2768.53   170.9  2771.6   174.8 2774.23
     184 2782.22   193.3 2783.49   205.2 2787.12   213.8 2788.57   222.4 2791.42
   230.3 2794.99   239.6 2796.59   245.8 2799.64   261.5 2804.15   279.4 2811.56
#Mann= 3, -1 ,  0
       0     0.1       0   140.8   0.045       0   151.8     0.1       0
Bank Sta=140.8,151.8
XS Rating Curve= 0 ,0
Exp/Cntr=0.3,0.1

Type RM Length L Ch R = 1 ,2815    ,226,224.6,222.3
XS GIS Cut Line= 2
2351950.53313192685055.6673181412352104.17356153685386.076844187
#Sta/Elev= 30
       0 2828.75    14.9 2822.91    19.3 2820.77    23.5 2818.47    32.5 2812.41
      37 2810.12    50.2 2806.04    63.4 2799.03    85.5 2790.72   125.2 2778.86
     134  2774.6   147.2 2766.28   151.7 2764.17   160.5 2761.11   164.9 2760.32
   182.5  2760.8   186.9 2760.21   195.8 2759.76  200.74 2760.19   207.1 2762.29
   226.6 2764.92   235.5 2767.96   244.3 2773.94   253.1 2778.05   269.5 2789.48
   282.4 2797.09   297.5 2803.46   319.3 2814.67   332.5 2819.19   364.4  2835.1
#Mann= 3, -1 ,  0
       0     0.1       0   186.9   0.045       0  200.74     0.1       0
Bank Sta=186.9,200.74
XS Rating Curve= 0 ,0
Exp/Cntr(USF)=0,0
Exp/Cntr=0.3,0.1

Type RM Length L Ch R = 1 ,2591    ,243.3,241.9,240.2
XS GIS Cut Line= 2
2351744.17586773685209.5766823422351929.97074156685444.091112346
#Sta/Elev= 30
       0 2809.74     8.3 2804.88    14.8 2801.76    32.2  2795.3    50.5 2787.62
    64.4 2782.43    73.7 2780.11    99.4 2771.64   106.7 2768.23   116.9 2760.94
     122 2759.31   132.2 2758.57   136.4 2757.31   142.1 2754.72     145 2754.25
   152.6 2753.74     161 2754.23   167.5 2756.07   176.3 2757.26   188.3 2761.44
   198.5 2765.55   213.8  2772.8     219  2774.5   238.3 2785.25   254.7 2792.96
   264.5 2798.27   278.8 2804.25   283.4 2806.74   290.4 2809.53   299.2 2813.82
#Mann= 3, -1 ,  0
       0     0.1       0     145   0.045       0     161     0.1       0
Bank Sta=145,161
XS Rating Curve= 0 ,0
Exp/Cntr=0.3,0.1

Type RM Length L Ch R = 1 ,2349    ,263.3,261.7,260.5
XS GIS Cut Line= 2
2351520.47549179685366.5258624832351779.84696974685584.596149674
#Sta/Elev= 30
       0 2820.75     4.8 2817.55    15.3 2812.76    25.7 2805.38    53.8 2792.11
    69.8 2782.43    72.6 2781.26    78.7 2780.76    83.2 2779.34    93.7 2772.61
   103.6 2770.77   106.7 2769.69   128.4  2758.2   134.7    2756   145.9 2751.01
   151.2 2747.43   153.3  2746.6   160.7  2746.2   168.6  2746.6   191.9 2749.58
   208.9 2748.92   213.9 2750.38   228.8 2758.17   246.5 2768.55   265.2 2777.29
   271.4 2779.71   281.8 2784.94   297.5 2791.06   318.4 2800.57   338.9 2811.78
#Mann= 3, -1 ,  0
       0     0.1       0   153.3   0.045       0   168.6     0.1       0
Bank Sta=153.3,168.6
XS Rating Curve= 0 ,0
Exp/Cntr(USF)=0,0
Exp/Cntr=0.3,0.1

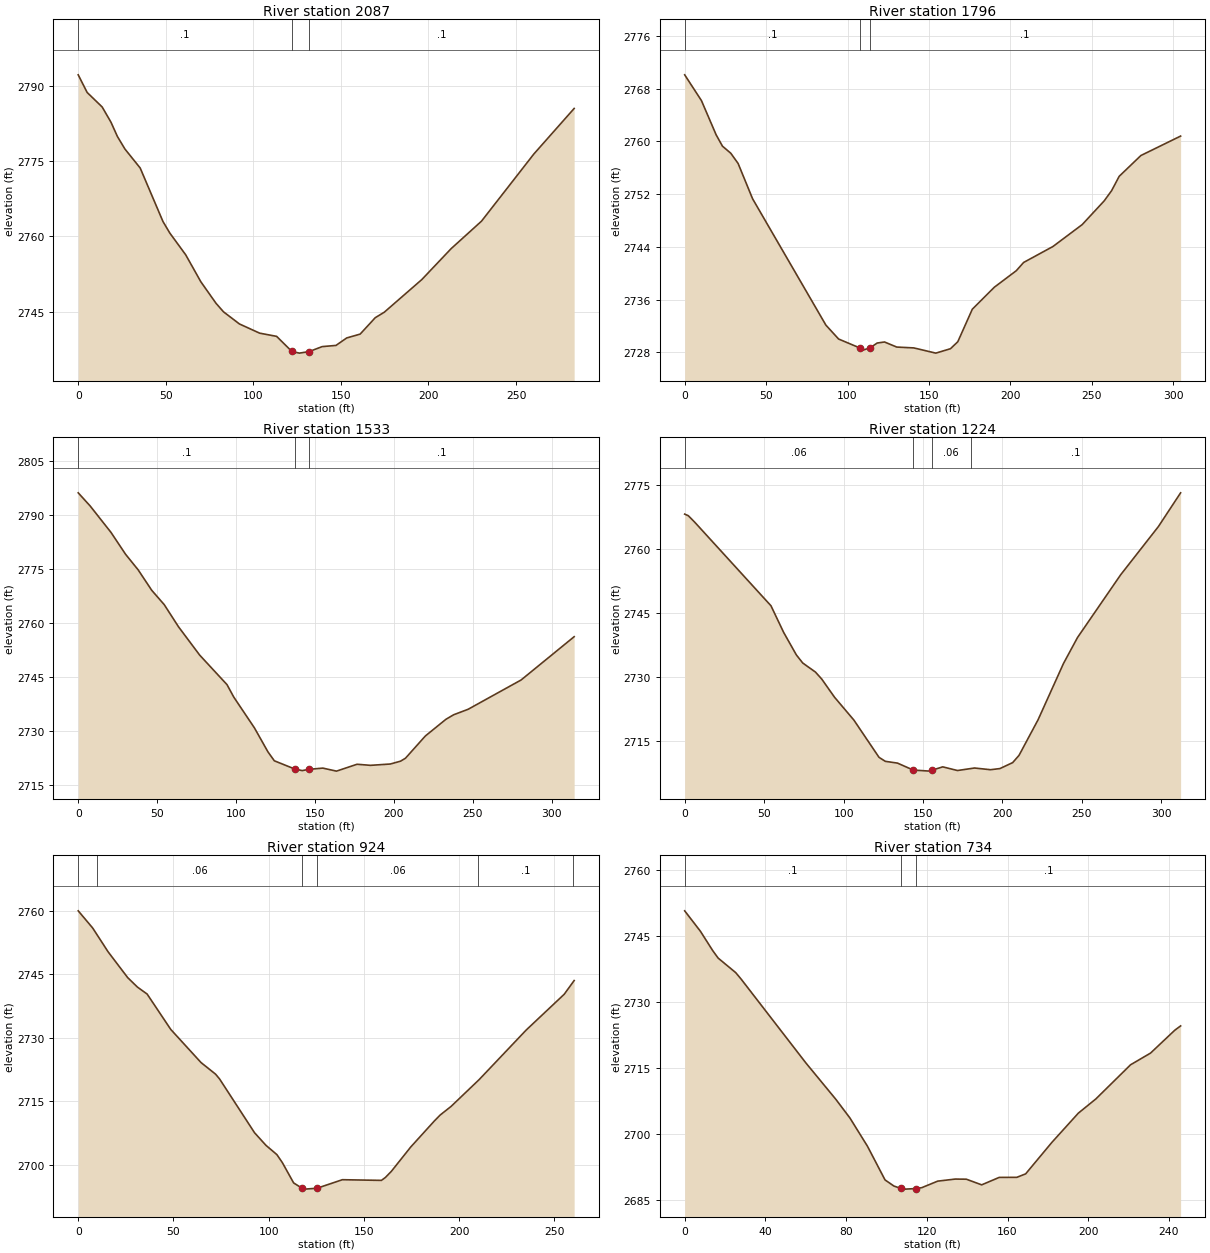
Type RM Length L Ch R = 1 ,2087    ,290,290.7,291
XS GIS Cut Line= 2
2351359.47869997685621.4933507982351621.08896128685729.975536284
#Sta/Elev= 30
       0 2792.29     5.1 2788.77    13.7 2785.86    18.7 2782.83    22.4 2779.96
    26.7 2777.46    35.4 2773.67    48.4 2762.99    52.3 2760.69    61.4 2756.33
      70 2750.97    78.7 2746.65      83 2744.94    92.1 2742.52   103.6 2740.69
   113.3 2740.05     122 2737.04   126.3  2736.7   131.9 2737.01   139.3    2738
   147.2 2738.24   153.3 2739.73     161  2740.5   169.6 2743.77   174.8 2744.88
   196.2 2751.39   212.9 2757.55   230.3 2763.06   260.2 2776.48   283.2 2785.57
#Mann= 3, -1 ,  0
       0     0.1       0     122   0.045       0   131.9     0.1       0
Bank Sta=122,131.9
XS Rating Curve= 0 ,0
Exp/Cntr=0.3,0.1

Type RM Length L Ch R = 1 ,1796    ,265.9,263,260.3
XS GIS Cut Line= 2
2351243.03972064685871.0373345412351513.89788576686010.146353198
#Sta/Elev= 30
       0 2770.09    10.3 2766.18    19.3    2761    23.2 2759.27    28.3  2758.2
    32.8 2756.65    41.7 2751.29    86.7 2732.13    94.5 2730.02   107.62728.657
   109.8 2728.37   113.7 2728.66   118.2 2729.41   122.7 2729.57   130.2  2728.8
   140.7 2728.67   154.2 2727.88   163.2 2728.55   167.7 2729.61   176.6 2734.54
   190.1 2737.87   203.6 2740.38   208.1 2741.63   226.1 2744.05   244.1 2747.38
   257.6 2750.98   262.1 2752.51   266.8  2754.7   280.1 2757.85   304.5  2760.8
#Mann= 3, -1 ,  0
       0     0.1       0   107.6   0.045       0   113.7     0.1       0
Bank Sta=107.6,113.7
XS Rating Curve= 0 ,0
Exp/Cntr(USF)=0,0
Exp/Cntr=0.3,0.1

Type RM Length L Ch R = 1 ,1533    ,307,309,311.4
XS GIS Cut Line= 2
2351249.14807497686217.404906453 2351539.1742145686096.254746903
#Sta/Elev= 30
       0 2796.25     7.6 2792.58    20.8 2785.22      30 2779.16      38 2774.81
    46.6 2769.12    54.5 2765.14    63.6 2758.95      77 2751.08    94.3 2742.87
    98.6  2739.4   111.7 2730.82   120.3 2724.12   124.3 2721.67   137.7 2719.31
     142 2718.95   146.3  2719.3     155 2719.64   163.7  2718.8   176.7 2720.71
   185.3 2720.41   197.8 2720.78   204.3 2721.57   207.4 2722.39     220 2728.58
     233 2733.21   237.9 2734.48   247.1 2736.01   280.7 2744.17   314.3 2756.21
#Mann= 3, -1 ,  0
       0     0.1       0   137.7   0.045       0   146.3     0.1       0
Bank Sta=137.7,146.3
XS Rating Curve= 0 ,0
Exp/Cntr(USF)=0,0
Exp/Cntr=0.3,0.1

Type RM Length L Ch R = 1 ,1224    ,297,300.2,307
XS GIS Cut Line= 2
2351345.86122453686422.512121537 2351657.9146658686429.854555449
#Sta/Elev= 30
       0 2768.06     2.3 2767.69     6.3 2766.18    54.3  2746.6    62.3 2740.35
    70.3 2735.08    74.3 2733.19    82.3 2731.07    86.3 2729.41    94.3 2725.18
   106.5 2719.82   122.3  2711.1   126.3 2710.16   133.9 2709.75   143.92708.113
   154.4 2707.87   155.52708.068   162.4 2708.87   171.7 2708.01   182.4  2708.6
   192.5  2708.2   198.4 2708.47   206.4 2709.86   210.4 2711.56   222.4  2719.9
   238.4 2733.09   247.2 2739.15   274.4 2753.87   298.1 2765.14   312.1 2773.05
#Mann= 4, -1 ,  0
       0    0.06       0   143.9   0.045       0   155.5    0.06       0
     180     0.1       0
Bank Sta=143.9,155.5
XS Rating Curve= 0 ,0
Exp/Cntr(USF)=0,0
Exp/Cntr=0.3,0.1

Type RM Length L Ch R = 1 ,924     ,189.1,190.3,191.2
XS GIS Cut Line= 2
2351201.78484387686524.9033192752351364.57989864686728.149746066
#Sta/Elev= 30
       0 2759.93     7.6 2755.88    15.7 2750.27      26 2744.18    31.1 2741.96
    36.2 2740.31    48.6 2731.98    64.5 2724.17    72.1 2721.45    74.2 2720.33
    92.6 2707.63    98.6 2704.66   104.3 2702.49   107.2 2700.59   113.1 2695.82
   117.62694.539     119 2694.35   125.4 2694.56   138.7 2696.57   159.2 2696.41
   161.3  2697.1   164.4 2698.53   174.6 2704.28   186.9 2710.36     190 2711.79
   195.8 2713.85   210.5 2720.15   235.2 2731.83   255.2 2740.28   260.4  2743.5
#Mann= 6, -1 ,  0
       0     0.1       0      10    0.06       0   117.6   0.045       0
   125.4    0.06       0     210     0.1       0     260    0.06       0
Bank Sta=117.6,125.4
XS Rating Curve= 0 ,0
Exp/Cntr(USF)=0,0
Exp/Cntr=0.3,0.1

Type RM Length L Ch R = 1 ,734     ,211.2,211.2,209.9
XS GIS Cut Line= 2
 2351065.1268095686601.9217849942351162.05611519686827.782761688
#Sta/Elev= 30
       0 2750.64     7.8 2746.01    13.9 2741.62    16.6 2739.92    25.3 2736.63
      28 2735.15    60.1 2716.14    74.9 2707.92    81.9 2703.68    90.6 2697.27
    99.3 2689.64   103.7 2688.25   107.2  2687.7   109.2 2687.55   114.8 2687.68
   117.5 2687.88   125.4 2689.36   134.1 2689.83   139.6  2689.8   147.2 2688.52
   155.9 2690.21   164.6 2690.22     169 2691.01     182 2698.15   195.1 2704.77
   203.8    2708     221 2715.74   230.9 2718.39   242.9 2723.57   245.8 2724.55
#Mann= 3, -1 ,  0
       0     0.1       0   107.2   0.045       0   114.8     0.1       0
Bank Sta=107.2,114.8
XS Rating Curve= 0 ,0
Exp/Cntr(USF)=0,0
Exp/Cntr=0.3,0.1

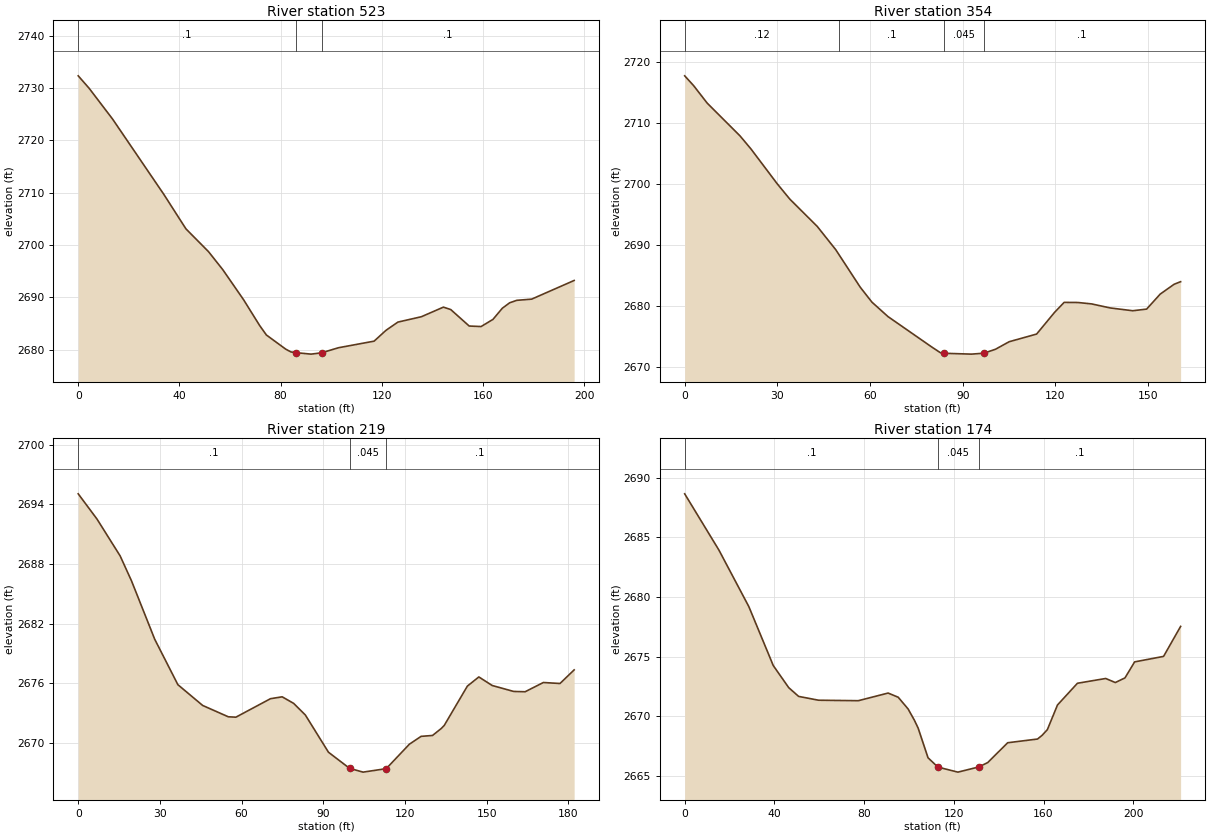
Type RM Length L Ch R = 1 ,523     ,170.3,168.6,164
XS GIS Cut Line= 2
2350897.17561641686733.5221646482350999.96969118 686900.56253615
#Sta/Elev= 30
       0 2732.36     4.3 2729.99    13.6 2724.09    33.9 2709.67    42.6 2703.11
    51.5 2698.77    57.2 2695.29    65.4 2689.56    71.7 2684.67    74.4 2682.83
      82 2680.14    84.1 2679.59    86.2 2679.44    92.1 2679.17    96.22679.416
   102.9 2680.39     117 2681.65   121.7 2683.72   126.4 2685.29   135.7 2686.32
   144.4 2688.15   147.3 2687.69   154.6 2684.54   159.3 2684.44     164 2685.81
   167.7 2687.94   170.6 2688.98   173.4 2689.45   179.3 2689.68   196.1 2693.25
#Mann= 3, -1 ,  0
       0     0.1       0    86.2   0.045       0    96.2     0.1       0
Bank Sta=86.2,96.2
XS Rating Curve= 0 ,0
Exp/Cntr(USF)=0,0
Exp/Cntr=0.3,0.1

Type RM Length L Ch R = 1 ,354     ,135.5,134.9,134
XS GIS Cut Line= 2
2350765.59460435686903.8802974372350910.11573104686973.732175338
#Sta/Elev= 30
       0 2717.66     2.9 2716.05     7.3 2713.18    17.9 2707.82    21.4 2705.71
    29.9    2700      34 2697.47    42.9 2692.98    48.9 2689.16    56.8 2683.03
    60.6 2680.57    65.8  2678.2    80.1 2673.17    82.8 2672.27    83.8 2672.19
    92.8 2672.05    96.82672.199   100.6 2672.85     105 2674.08   113.9 2675.34
   119.7 2678.89   122.8 2680.53   127.3 2680.51   131.7 2680.28   137.7 2679.62
     145 2679.16   149.5 2679.43   153.9 2681.89   158.4  2683.5   160.5 2683.92
#Mann= 4, -1 ,  0
       0    0.12       0      50     0.1       0    83.8   0.045       0
    96.8     0.1       0
Bank Sta=83.8,96.8
XS Rating Curve= 0 ,0
Exp/Cntr(USF)=0,0
Exp/Cntr=0.3,0.1

Type RM Length L Ch R = 1 ,219     ,44.7,45.4,46.4
XS GIS Cut Line= 2
2350689.72101283687029.1319405712350861.09898224 687090.79428796
#Sta/Elev= 30
       0 2695.07     6.9 2692.53    15.4 2688.82    19.6 2686.29    28.1 2680.43
    36.6 2675.86    45.7 2673.77    55.1 2672.63    57.9 2672.59    70.6 2674.45
    74.9 2674.64    79.1 2673.98    83.4 2672.81    91.9 2669.06   99.65 2667.44
   104.6 2667.06   113.1 2667.41   121.6 2669.87   125.9 2670.66   130.1 2670.75
   133.3 2671.45   134.4 2671.76   142.9 2675.72   147.1 2676.64     152 2675.78
   159.9 2675.18   164.1 2675.15   170.8 2676.08   176.9 2675.98   182.1 2677.35
#Mann= 3, -1 ,  0
       0     0.1       0   99.65   0.045       0   113.1     0.1       0
Bank Sta=99.65,113.1
XS Rating Curve= 0 ,0
Exp/Cntr(USF)=0,0
Exp/Cntr=0.3,0.1

Type RM Length L Ch R = 1 ,174     ,,,
XS GIS Cut Line= 3
 2350662.3774735 687054.316818152350814.61118242687127.438983442
2350863.21863853687108.428364843
#Sta/Elev= 30
       0 2688.64    15.3 2683.92    28.6  2679.2    39.5 2674.26    46.4 2672.41
    50.8 2671.68    59.7 2671.36    77.4 2671.32    90.7 2671.96    95.2 2671.61
    99.6 2670.63   102.4 2669.69   104.1 2669.02   108.5 2666.54   112.9 2665.76
   121.8 2665.34  131.05 2665.77   135.1 2666.14     144  2667.8   157.3 2668.11
   159.4 2668.43   161.7  2668.9   166.2 2670.96   175.1 2672.78   187.7 2673.18
     192 2672.84   196.3 2673.23   200.6 2674.57   213.5 2675.03   221.1 2677.54
#Mann= 3, -1 ,  0
       0     0.1       0   112.9   0.045       0  131.05     0.1       0
Bank Sta=112.9,131.05
XS Rating Curve= 0 ,0
Exp/Cntr(USF)=0,0
Exp/Cntr=0.3,0.1
LCMann Table=0

Chan Stop Cuts=-1
Use User Specified Reach Order=0
Composite Channel Slope=5